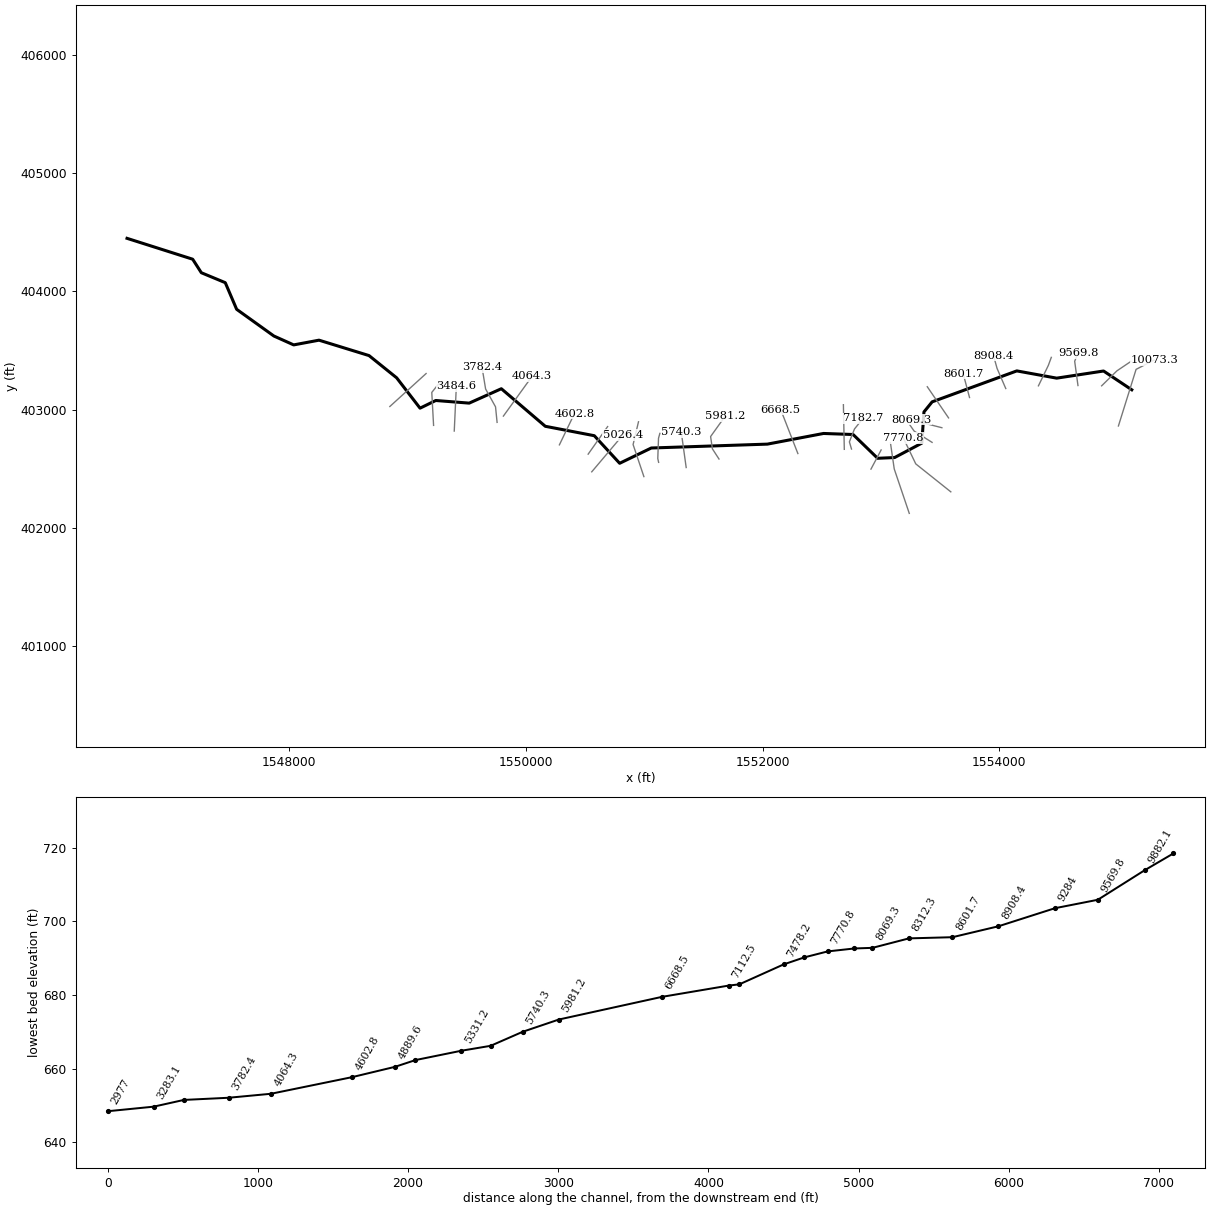
--- BILLYBR.prj (project) ---

Proj Title=BILLYBR
Current Plan=p01
Default Exp/Contr=0,0
English Units
Geom File=g01
Flow File=f01
Plan File=p01
BEGIN DESCRIPTION:
END DESCRIPTION:
DSS Export Rating Curves= 0
DSS Export Rating Curve Sorted= 0
DSS Export Volume Flow Curves= 0
DXF OffsetX= 0
DXF OffsetY= 0
DXF ScaleX= 0
DXF ScaleY= 0

--- BILLYBR.p01 (plan) ---

Plan Title=Floodplain
Program Version=4.00
Geom File=g01
Flow File=f01
K Sum by GR=0
Std Step Tol=0.01
Critical Tol=0.01
Num of Std Step Trials=20
Max Error Tol=0.3
Flow Tol Ratio=0.001
Split Flow NTrial=30
Split Flow Tol=0.02
Split Flow Ratio=0.02
Log Output Level=0
Friction Slope Method=1
Unsteady Friction Slope Method=2
Unsteady Bridges Friction Slope Method=1
Global Log Level=0
CheckData=False
Run HTab=0
Run UNet=0
Run PostProcess=0
UNET Theta=0
UNET Theta Warmup=0
UNET ZTol=0
UNET ZSATol=0
UNET MxIter=0
UNET MaxInSteps=0
UNET DtIC=0
UNET DtMin=0
UNET MaxCRTS=0
UNET WFStab=0
UNET SFStab=0
UNET WFX=0
UNET SFX=0
UNET DSS MLevel=0
UNET DZMax Abort=0
UNET Convert EG Bridges=0
UNET Use Existing IB Tables=0
UNET Froude Limit=0
UNET Froude Power=0
Write IC File=0
Echo Input=False
Echo Output=False
Write Detailed=0

--- BILLYBR.f01 (steady flow) ---

Flow Title=NFF Regression Equation
Program Version=4.00
Number of Profiles=1
Profile Names=P100yr
River Rch & RM=BILLYBR,Main      ,10073.3
346.9716
River Rch & RM=BILLYBR,Main      ,9882.1
357.6627
River Rch & RM=BILLYBR,Main      ,9569.8
419.7665
River Rch & RM=BILLYBR,Main      ,7770.8
459.5068
River Rch & RM=BILLYBR,Main      ,7478.2
586.1980
River Rch & RM=BILLYBR,Main      ,7182.7
597.4504
River Rch & RM=BILLYBR,Main      ,5740.3
657.0581
River Rch & RM=BILLYBR,Main      ,3283.1
727.5676
Boundary for River Rch & Prof#=BILLYBR,Main      ,1
Up Type=0
Dn Type=3
Dn Slope=0.005046

--- BILLYBR.g01 (geometry) ---

Geom Title=Geometry
Program Version=4.00

River Reach=BILLYBR         ,Main
Reach XY= 30
     1555120.436      403166.644     1554881.922       403325.45
     1554485.856      403265.135     1554148.828      403326.342
     1553433.302      403064.784     1553364.155      402979.602
     1553346.063      402715.934     1553116.351      402594.234
     1552972.741      402587.874     1552765.452      402788.839
     1552515.484      402797.682     1552041.157      402707.622
      1551060.11      402674.817     1550792.671      402545.677
     1550578.459      402778.761     1550164.331      402858.344
     1549792.882      403175.768      1549521.28      403054.085
      1549238.67      403076.293     1549105.843      403011.408
     1548908.213      403267.941     1548674.867      403455.806
     1548252.076      403586.034     1548038.206      403546.119
     1547870.679       403621.23     1547556.118      403846.894
     1547460.048      404071.981     1547257.739      404156.008
     1547184.525      404270.233     1546629.719      404446.651

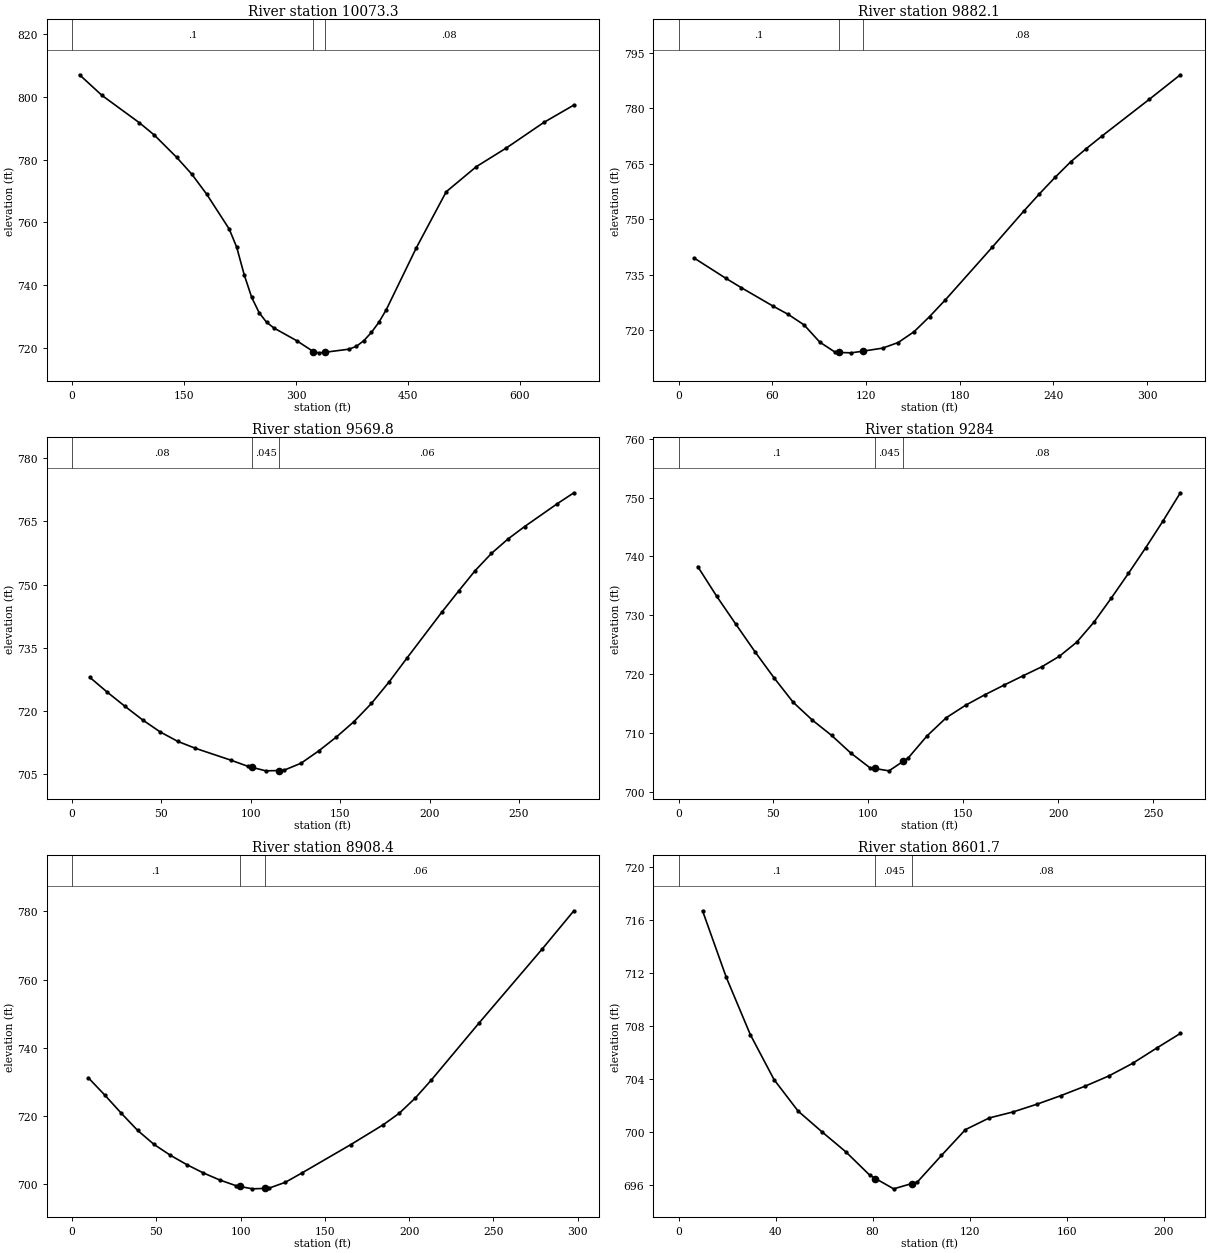
Type RM Length L Ch R = 1 ,10073.3 ,202.5,191.2,179.8
XS GIS Cut Line= 3
     1555007.459      402860.967     1555156.822      403339.433
     1555308.716      403417.911
#Sta/Elev= 30
      10  807.03    40.1  800.45    90.2  791.74   110.3   787.8   140.3  780.68
   160.4  775.36   180.4  768.96   210.5  757.89   220.5  752.13   230.6   743.3
   240.6  736.12   250.6  731.22   260.6  728.17   270.7  726.31   300.7  722.34
   323.3  718.83   330.8  718.44   338.3   718.6   370.9  719.61   380.9  720.52
     391  722.35     401  724.95     411  728.17     421  732.23   461.1  751.87
   501.2  769.76   541.5  777.75   581.7   783.7     632  791.85   672.2  797.38
#Mann= 3 , 0 , 0
       0      .1       0   323.3    .045       0   338.3     .08       0
Bank Sta=323.3,338.3
XS Rating Curve= 0 ,0
Exp/Cntr=0.3,0.1

Type RM Length L Ch R = 1 ,9882.1  ,291.2,312.3,333.5
XS GIS Cut Line= 3
     1554865.692      403200.197     1554994.802      403326.775
     1555111.254      403405.254
#Sta/Elev= 25
      10   739.5    30.1  734.08    40.2  731.49    60.3  726.56    70.3  724.25
    80.4  721.42    90.4  716.78   100.4  714.01     103  713.98   110.5  713.88
     118  714.33   130.6  715.15   140.6  716.67   150.7  719.57   160.7  723.68
   170.8   728.2   200.9  742.48   220.9  752.15     231  756.86     241  761.31
     251  765.51   261.1  769.12   271.1  772.51   301.2  782.37   321.2  789.05
#Mann= 3 , 0 , 0
       0      .1       0     103    .045       0     118     .08       0
Bank Sta=103,118
XS Rating Curve= 0 ,0
Exp/Cntr=0.3,0.1

Type RM Length L Ch R = 1 ,9569.8  ,299.2,285.8,272.4
XS GIS Cut Line= 3
     1554665.698      403202.728     1554637.851      403407.785
     1554665.698      403476.138
#Sta/Elev= 28
     9.9  728.02    19.7  724.49    29.6  721.14    39.4  717.94    49.3  715.07
    59.1  712.84      69  711.19    88.7   708.4    98.5   706.9   100.9  706.65
   108.4  705.85   115.9  705.92   118.3  705.95   128.1  707.66     138  710.58
   147.8  713.85   157.7  717.52   167.5  721.84   177.4  726.95   187.2   732.5
   206.9  743.49   216.2  748.44   225.4  753.26   234.6  757.38   243.8  760.78
   253.1  763.73   271.5  769.18   280.7  771.75
#Mann= 3 , 0 , 0
       0     .08       0   100.9    .045       0   115.9     .06       0
Bank Sta=100.9,115.9
XS Rating Curve= 0 ,0
Exp/Cntr=0.3,0.1

Type RM Length L Ch R = 1 ,9284    ,356,375.6,395.3
XS GIS Cut Line= 3
     1554331.531      403200.197     1554415.073      403372.343
     1554440.388      403440.696
#Sta/Elev= 29
    10.1  738.28    20.1  733.23    30.2  728.47    40.3  723.78    50.4  719.32
    60.4   715.2    70.5  712.17    80.6  709.58    90.6  706.61   100.7   704.1
   103.3  703.96   110.8  703.56   118.3  705.18   120.9  705.74   130.9  709.52
     141   712.6   151.1   714.7   161.1  716.46   171.2   718.1   181.3   719.7
   191.3  721.25   200.5  723.03   209.6  725.41   218.7  728.82   227.8   732.9
   236.9  737.13     246  741.49   255.1  746.04   264.2  750.82
#Mann= 3 , 0 , 0
       0      .1       0   103.3    .045       0   118.3     .08       0
Bank Sta=103.3,118.3
XS Rating Curve= 0 ,0
Exp/Cntr=0.3,0.1

Type RM Length L Ch R = 1 ,8908.4  ,310,306.7,303.3
XS GIS Cut Line= 3
      1554055.59      403177.413     1553982.175      403347.028
     1553951.796      403455.885
#Sta/Elev= 24
     9.7  731.18    19.5  726.09    29.2  720.82    38.9  715.79    48.6  711.69
    58.4  708.48    68.1  705.75    77.8  703.35    87.5  701.28    97.3  699.58
    99.5  699.37     107  698.66   114.5  698.79   116.7  698.83   126.5  700.56
   136.2  703.25   165.4  711.62   184.8  717.48   194.2  720.82   203.7  725.27
   213.1  730.48   241.3  747.12     279  768.93   297.8  780.14
#Mann= 3 , 0 , 0
       0      .1       0    99.5    .045       0   114.5     .06       0
Bank Sta=99.5,114.5
XS Rating Curve= 0 ,0
Exp/Cntr=0.3,0.1

Type RM Length L Ch R = 1 ,8601.7  ,281.8,289.4,297
XS GIS Cut Line= 2
     1553749.271      403101.466     1553696.108      403301.459
#Sta/Elev= 23
     9.9  716.68    19.7  711.65    29.6  707.33    39.4  703.93    49.3  701.56
    59.1     700      69  698.48    78.8  696.73    81.2  696.47    88.7  695.69
    96.2  696.09    98.5  696.21   108.4  698.21   118.3  700.16   128.1  701.04
     138   701.5   147.8  702.08   157.7  702.73   167.5  703.43   177.4  704.21
   187.2  705.16   197.1  706.31   206.9  707.42
#Mann= 3 , 0 , 0
       0      .1       0    81.2    .045       0    96.2     .08       0
Bank Sta=81.2,96.2
XS Rating Curve= 0 ,0
Exp/Cntr=0.3,0.1

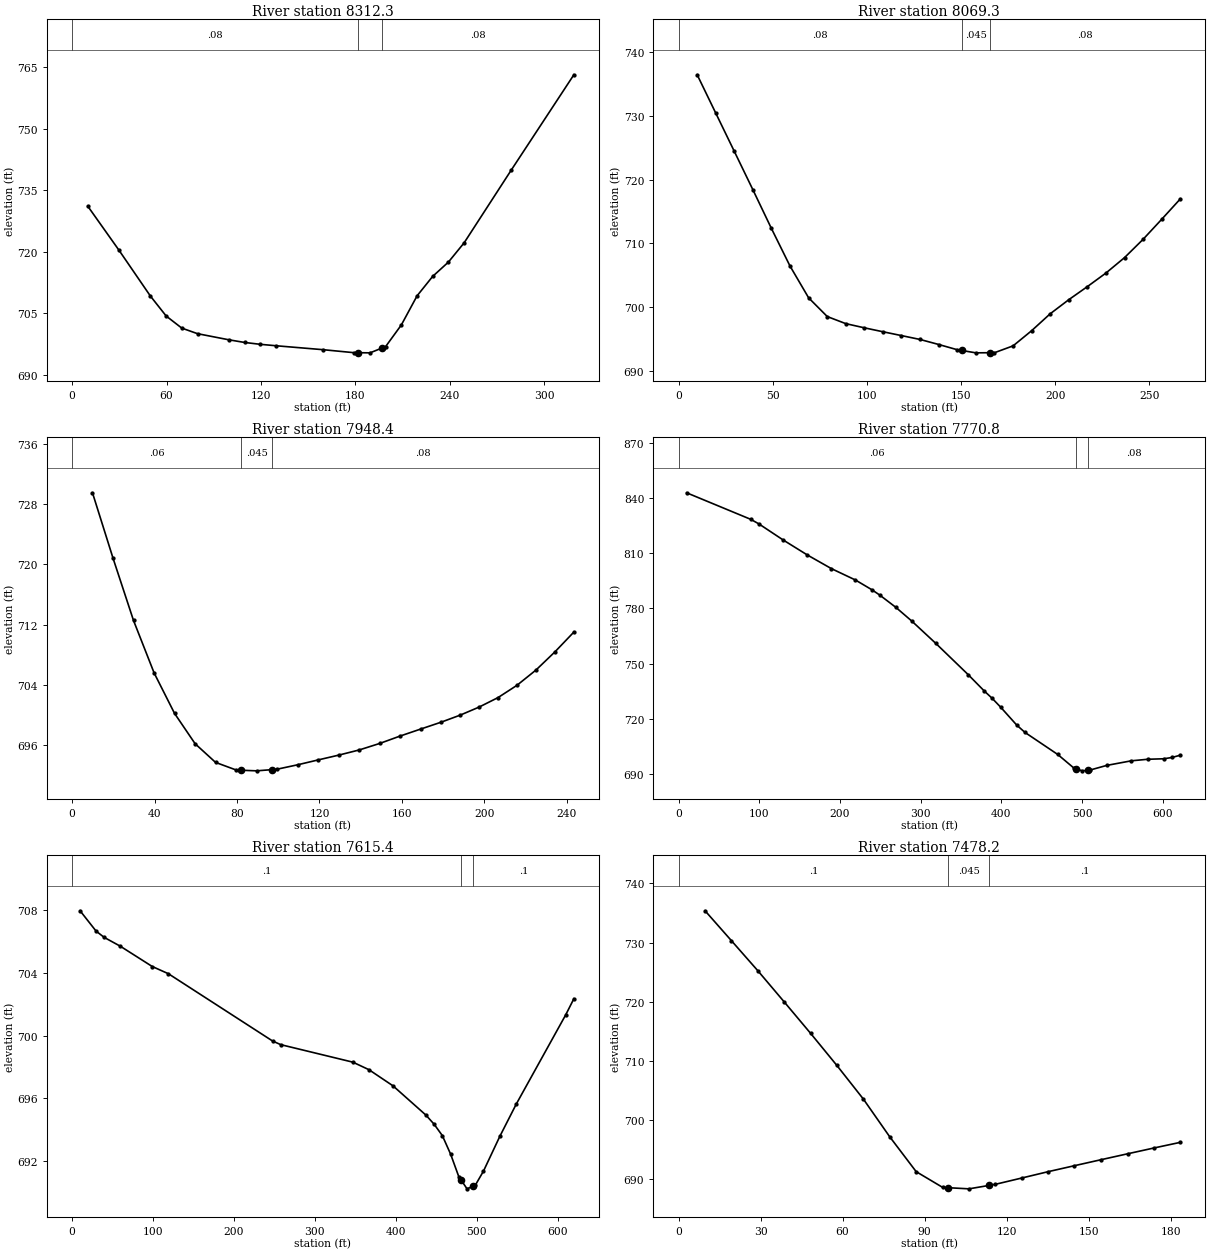
Type RM Length L Ch R = 1 ,8312.3  ,226.6,243,259.5
XS GIS Cut Line= 2
     1553572.061      402929.319      1553392.32      403192.602
#Sta/Elev= 23
      10   731.1    29.9  720.33    49.8  709.19    59.8  704.34    69.7   701.4
    79.7  700.04    99.6  698.55   109.6   697.9   119.5  697.45   129.5   697.1
   159.4  696.14   179.3   695.4   181.8   695.4   189.3  695.37   196.8  696.52
   199.2  696.89   209.2  702.17   219.2  709.27   229.1     714   239.1  717.49
   249.1  722.19   278.9  739.84   318.8  763.14
#Mann= 3 , 0 , 0
       0     .08       0   181.8    .045       0   196.8     .08       0
Bank Sta=181.8,196.8
XS Rating Curve= 0 ,0
Exp/Cntr=0.3,0.1

Type RM Length L Ch R = 1 ,8069.3  ,128.4,120.9,113.3
XS GIS Cut Line= 2
     1553515.655        402846.3     1553257.435      402912.121
#Sta/Elev= 29
     9.9  736.49    19.7  730.51    29.6  724.47    39.5  718.42    49.3  712.36
    59.2  706.44    69.1  701.44      79   698.5    88.8  697.39    98.7  696.73
   108.6  696.11   118.4  695.51   128.3   694.9   138.2  694.11     148  693.29
   150.4  693.17   157.9   692.8   165.4  692.82   167.8  692.82   177.7   693.9
   187.5  696.27   197.4  698.94   207.3  701.16   217.1   703.2     227  705.34
   236.9  707.77   246.7  710.63   256.6  713.78   266.5  716.99
#Mann= 3 , 0 , 0
       0     .08       0   150.4    .045       0   165.4     .08       0
Bank Sta=150.4,165.4
XS Rating Curve= 0 ,0
Exp/Cntr=0.3,0.1

Type RM Length L Ch R = 1 ,7948.4  ,189.9,177.5,165.2
XS GIS Cut Line= 3
     1553432.922      402722.427     1553281.285      402817.663
     1553244.506      402870.426
#Sta/Elev= 27
     9.9   729.5    19.9   720.8    29.8  712.57    39.8  705.61    49.7  700.25
    59.7  696.22    69.6  693.75    79.6  692.74      82  692.71    89.5  692.63
      97  692.79    99.5  692.85   109.4  693.43   119.4  694.08   129.3  694.71
   139.3   695.4   149.2  696.26   159.2  697.25   169.1  698.17   179.1  699.09
   188.3  700.02   197.4  701.08   206.6  702.34   215.8  703.97     225  705.99
   234.2   708.4   243.4  711.03
#Mann= 3 , 0 , 0
       0     .06       0      82    .045       0      97     .08       0
Bank Sta=82,97
XS Rating Curve= 0 ,0
Exp/Cntr=0.3,0.1

Type RM Length L Ch R = 1 ,7770.8  ,162.2,155.4,148.6
XS GIS Cut Line= 3
     1553591.148      402304.413      1553294.97      402540.589
     1553189.794      402759.704
#Sta/Elev= 30
      10  842.82    89.7  828.36    99.7  825.89   129.6  817.21   159.5  809.08
   189.4  801.65   219.3  795.44   239.3  790.25   249.2  787.33   269.2  780.65
   289.1  773.15     319  760.98   358.9   744.1   378.8  735.24   388.9  731.12
   399.1  726.46   419.3   716.6   429.5  712.65     470  700.71   490.2  693.26
   492.8  692.89   500.3  691.83   507.8  692.19   510.5  692.32   530.7  694.78
   561.1  697.27   581.4  698.11   601.6  698.39   611.7   699.1   621.9  700.33
#Mann= 3 , 0 , 0
       0     .06       0   492.8    .045       0   507.8     .08       0
Bank Sta=492.8,507.8
XS Rating Curve= 0 ,0
Exp/Cntr=0.3,0.1

Type RM Length L Ch R = 1 ,7615.4  ,151.5,137.2,123
XS GIS Cut Line= 3
     1553240.082      402122.378     1553113.044      402498.019
     1553080.937      402719.199
#Sta/Elev= 25
     9.9  707.97    29.7  706.67    39.7  706.27    59.5  705.71    99.1  704.41
     119  703.95   247.8  699.65   257.8  699.42     347   698.3   366.8  697.82
   396.5  696.79   437.2  694.92   447.3  694.34   457.5  693.61   467.7  692.43
   477.8  690.99   480.5  690.79     488  690.21   495.5  690.38   498.1  690.43
   508.3  691.34   528.6  693.57   548.9  695.63   609.9  701.32     620  702.35
#Mann= 3 , 0 , 0
       0      .1       0   480.5    .045       0   495.5      .1       0
Bank Sta=480.5,495.5
XS Rating Curve= 0 ,0
Exp/Cntr=0.3,0.1

Type RM Length L Ch R = 1 ,7478.2  ,293.1,295.5,297.9
XS GIS Cut Line= 2
     1552916.385      402496.421     1553002.458      402658.441
#Sta/Elev= 21
     9.7  735.38    19.3  730.34      29  725.23    38.6  719.98    48.3  714.63
    57.9   709.2    67.6   703.5    77.2  697.14    86.9  691.22    96.6  688.55
    98.7   688.5   106.2  688.31   113.7   688.9   115.9  689.08   125.5  690.14
   135.2  691.22   144.8  692.23   154.5  693.24   164.2  694.24   173.8  695.22
   183.5  696.18
#Mann= 3 , 0 , 0
       0      .1       0    98.7    .045       0   113.7      .1       0
Bank Sta=98.7,113.7
XS Rating Curve= 0 ,0
Exp/Cntr=0.3,0.1

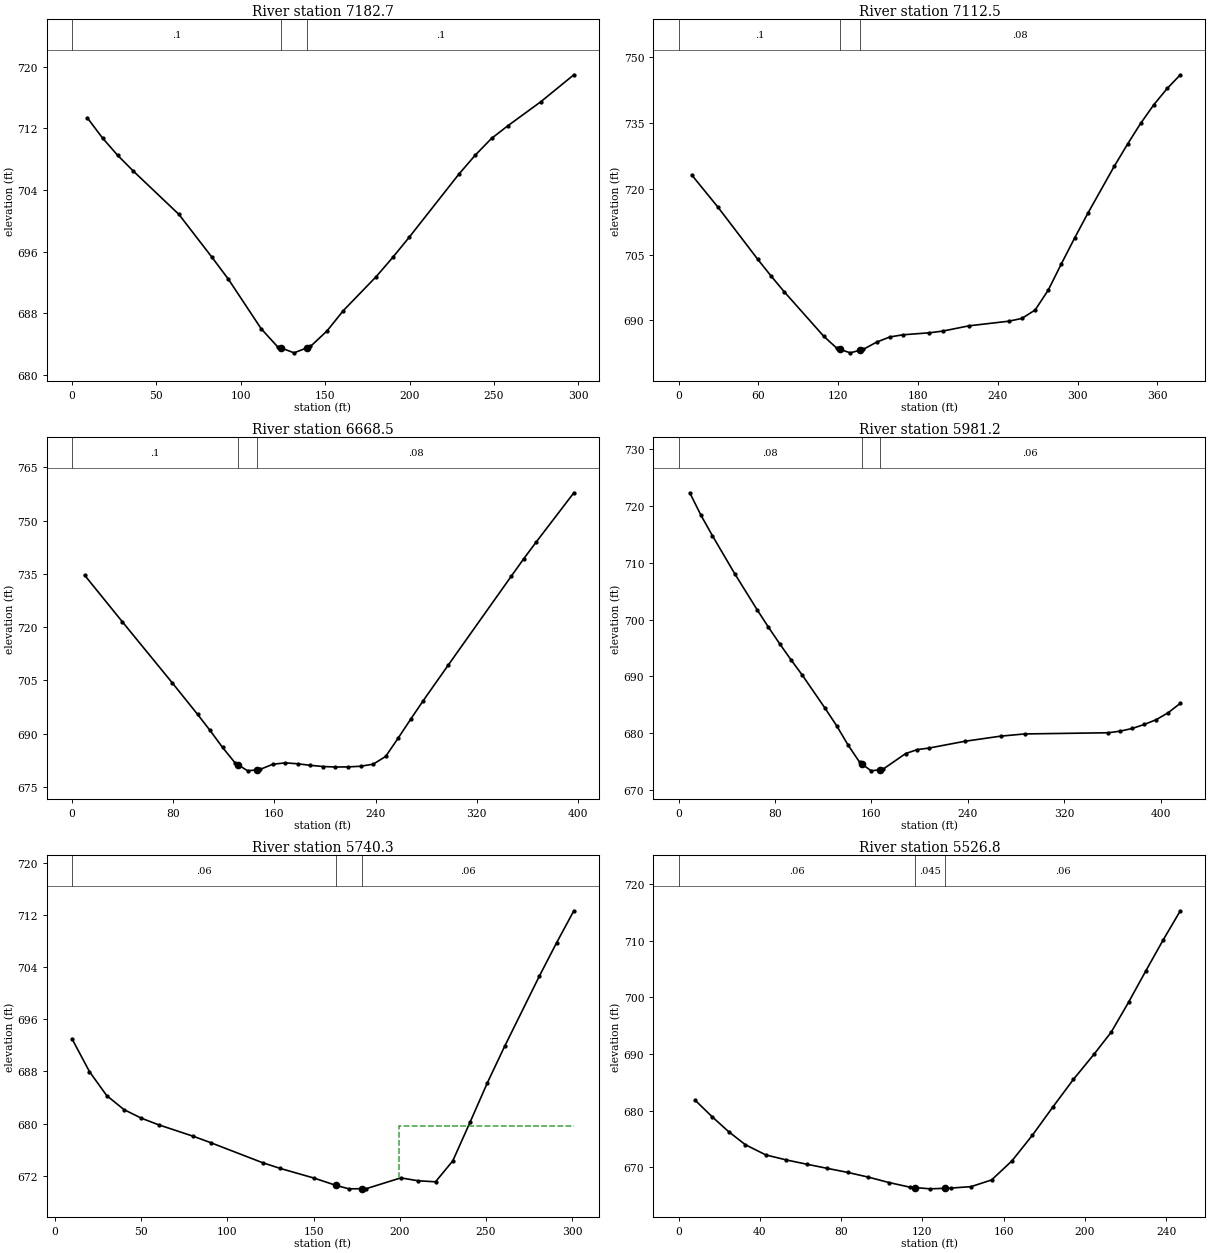
Type RM Length L Ch R = 1 ,7182.7  ,60.9,70.2,79.5
XS GIS Cut Line= 4
     1552751.833      402666.036     1552734.112      402726.794
     1552777.149      402835.651     1552850.564      402926.788
#Sta/Elev= 24
       9  713.36    18.1  710.72    27.1  708.47    36.2  706.47    63.3  700.84
    82.8  695.31    92.6  692.45   112.1  686.01   121.8  683.68   124.1   683.5
   131.6  682.89   139.1  683.53   141.3  683.72   151.1  685.73   160.8  688.37
   180.3  692.78   190.1  695.27   199.8  697.87   229.1  706.01   238.9   708.5
   248.6  710.68   258.4  712.34   277.9  715.45   297.4  718.93
#Mann= 3 , 0 , 0
       0      .1       0   124.1    .045       0   139.1      .1       0
Bank Sta=124.1,139.1
XS Rating Curve= 0 ,0
Exp/Cntr=0.3,0.1

Type RM Length L Ch R = 1 ,7112.5  ,436,444,451.9
XS GIS Cut Line= 2
     1552691.076      402663.505     1552683.481      403040.708
#Sta/Elev= 30
     9.9  723.19    29.8  715.76    59.6   703.9    69.5  700.13    79.4  696.53
   109.2  686.34   119.1  683.59   121.6  683.33   129.1  682.56   136.6  683.17
     139  683.37   148.9     685   158.9  686.19   168.8  686.68   188.6  687.14
   198.6  687.52   218.4  688.73   248.2  689.78   258.1  690.41   268.1  692.33
     278  696.89   287.9  702.92   297.9  708.82   307.8  714.45   327.6  725.15
   337.6  730.21   347.5  734.97   357.4  739.22   367.4  742.92   377.3  746.05
#Mann= 3 , 0 , 0
       0      .1       0   121.6    .045       0   136.6     .08       0
Bank Sta=121.6,136.6
XS Rating Curve= 0 ,0
Exp/Cntr=0.3,0.1

Type RM Length L Ch R = 1 ,6668.5  ,692.4,687.3,682.2
XS GIS Cut Line= 2
     1552298.683      402628.063     1552154.384      402997.671
#Sta/Elev= 29
     9.9  734.61    39.7   721.5    79.4  704.21    99.2  695.43   109.1  690.88
     119  686.09     129   681.7   131.4  681.17   138.9   679.5   146.4  679.81
   148.8  679.92   158.7  681.35   168.6  681.75   178.6  681.48   188.5  681.05
   198.4  680.72   208.3  680.58   218.2  680.61   228.1  680.79   238.1  681.37
     248  683.56   257.9  688.74   267.8  694.06   277.7  699.27   297.6  709.35
   347.2  734.26   357.1   739.2     367  743.93   396.8  757.81
#Mann= 3 , 0 , 0
       0      .1       0   131.4    .045       0   146.4     .08       0
Bank Sta=131.4,146.4
XS Rating Curve= 0 ,0
Exp/Cntr=0.3,0.1

Type RM Length L Ch R = 1 ,5981.2  ,241.1,240.9,240.7
XS GIS Cut Line= 4
     1551632.125      402581.765     1551576.431      402667.839
     1551561.242      402771.633     1551682.757      402941.248
#Sta/Elev= 30
     9.3  722.33    18.6  718.37      28   714.8    46.6  708.07    65.2  701.71
    74.6  698.64    83.9  695.72    93.2  692.92   102.5  690.24   121.6  684.34
   131.1  681.29   140.7  677.85   150.2  674.85   152.2  674.53   159.7  673.34
   167.2  673.54   169.3  673.59   188.3  676.38   197.9  677.08   207.4  677.34
   237.2  678.54     267  679.45   286.9  679.84   356.5  680.05   366.4  680.34
   376.3  680.81   386.3  681.52   396.2  682.36   406.1  683.59   416.1  685.24
#Mann= 3 , 0 , 0
       0     .08       0   152.2    .045       0   167.2     .06       0
Bank Sta=152.2,167.2
XS Rating Curve= 0 ,0
Exp/Cntr=0.3,0.1

Type RM Length L Ch R = 1 ,5740.3  ,217.4,213.5,209.6
XS GIS Cut Line= 2
     1551354.921      402509.781     1551313.579      402807.876
#Sta/Elev= 25
      10  692.98    20.1  687.96    30.1  684.29    40.1  682.15    50.2  680.83
    60.2  679.82    80.3  678.06    90.3  677.09   120.4  674.02   130.4  673.16
   150.5  671.64     163  670.54   170.5  670.01     178  670.03   180.6  670.04
   200.6  671.69   210.7  671.24   220.7  671.09   230.7  674.29   240.8  680.26
   250.8  686.28   260.8  691.86   280.9   702.6   290.9  707.72   300.9  712.61
#Mann= 3 , 0 , 0
      10     .06       0     163    .045       0     178     .06       0
#XS Ineff= 2 , 0
                          199.66          679.59
Permanent Ineff=
       F       F
Bank Sta=163,178
XS Rating Curve= 0 ,0
Exp/Cntr=0.3,0.1

Type RM Length L Ch R = 1 ,5526.8  ,187.4,195.5,203.6
XS GIS Cut Line= 4
     1551121.973       402553.67      1551115.01      402585.873
     1551121.103      402757.332     1551132.417      402798.239
#Sta/Elev= 28
     8.2  681.83    16.5  678.94    24.7  676.28    32.9  673.99      43  672.18
    53.1   671.3    63.2  670.54    73.3  669.81    83.4  669.09    93.5  668.26
   103.6  667.31   113.7  666.51   116.3  666.43   123.8   666.2   131.3   666.3
   133.9  666.33     144  666.59   154.1  667.77   164.1  671.13   174.2  675.67
   184.3  680.67   194.4  685.53   204.5  689.95     213  693.87   221.5  699.12
     230  704.66   238.5   710.1     247  715.28
#Mann= 3 , 0 , 0
       0     .06       0   116.3    .045       0   131.3     .06       0
Bank Sta=116.3,131.3
XS Rating Curve= 0 ,0
Exp/Cntr=0.3,0.1

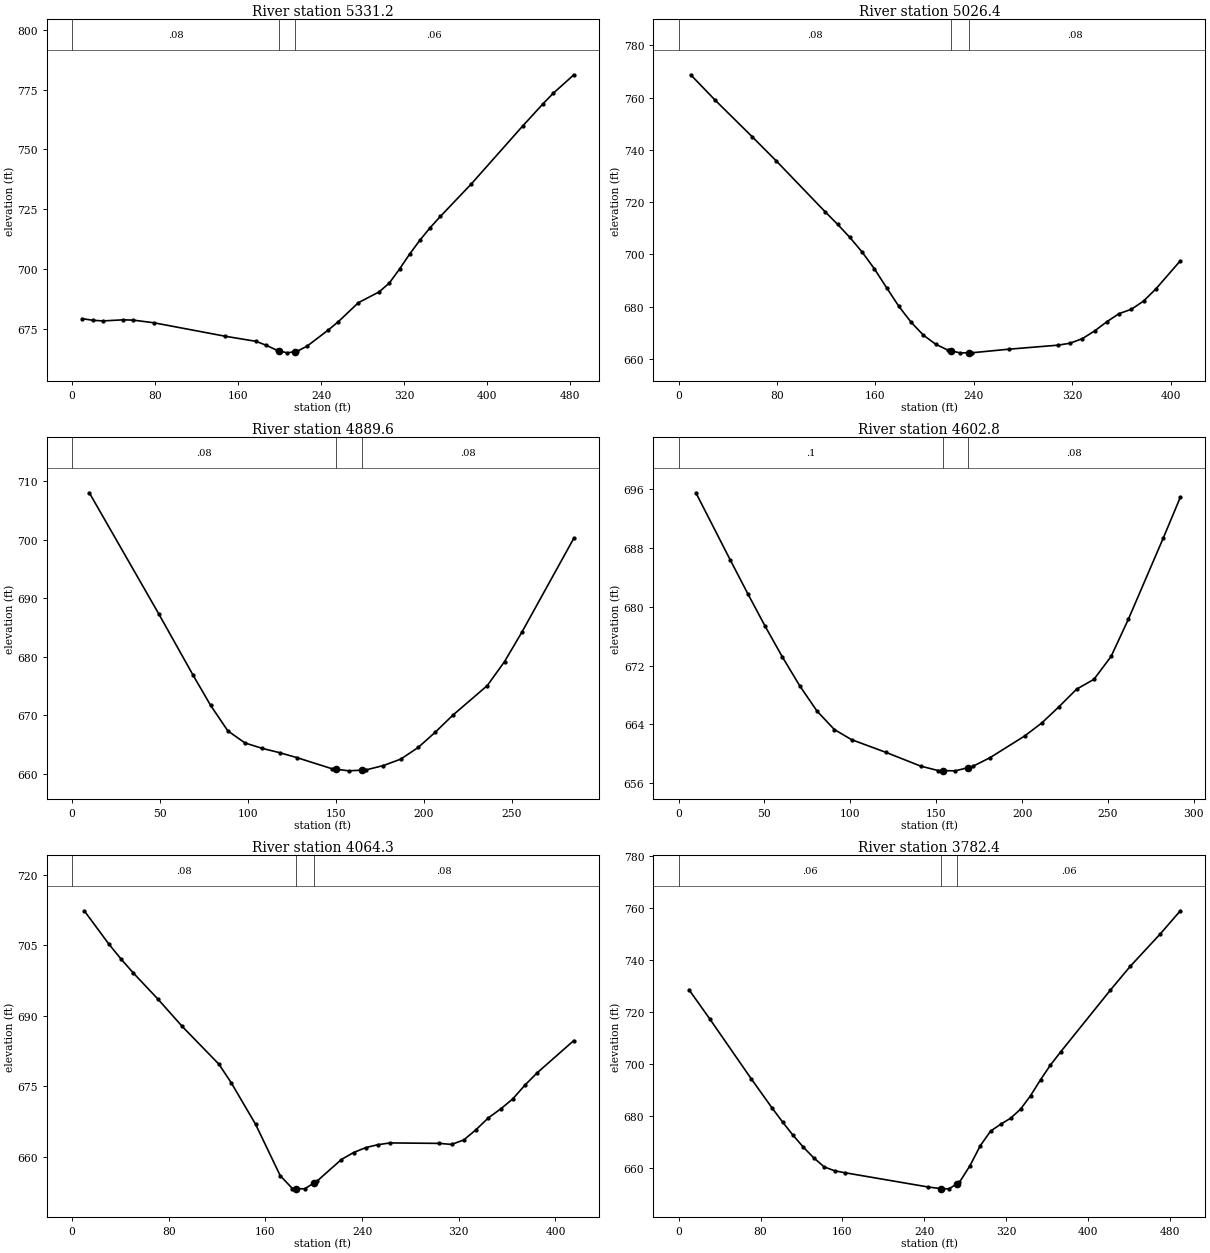
Type RM Length L Ch R = 1 ,5331.2  ,328.3,304.9,281.4
XS GIS Cut Line= 3
     1550997.458      402433.132     1550906.321       402704.01
     1550951.889      402896.409
#Sta/Elev= 30
     9.9  679.18    19.7   678.5    29.6  678.22    49.3  678.68    59.1  678.55
    78.8  677.45   147.8  671.79   177.4  669.66   187.2  668.01   197.1     666
   199.5  665.72     207  664.86   214.5  665.33   216.8  665.47   226.7  667.74
   246.4  674.26   256.2  677.76   275.9  685.86   295.7  690.33   305.6  694.04
   315.5  699.91   325.3  706.22   335.2  712.05   345.1   717.3     355  722.02
   384.7  735.58   434.1  759.78   453.9  769.18   463.7  773.55   483.5  781.27
#Mann= 3 , 0 , 0
       0     .08       0   199.5    .045       0   214.5     .06       0
Bank Sta=199.5,214.5
XS Rating Curve= 0 ,0
Exp/Cntr=0.3,0.1

Type RM Length L Ch R = 1 ,5026.4  ,135.1,136.8,138.4
XS GIS Cut Line= 2
     1550556.965      402473.637     1550820.248       402785.02
#Sta/Elev= 30
     9.9  768.72    29.8  758.99    59.7  745.09    79.6  735.68   119.3  716.23
   129.3  711.49   139.2  706.51   149.2   700.9   159.1  694.52   169.1  687.25
     179  680.16     189  674.05   198.9  669.13   208.9  665.65   218.8  663.39
   221.2  663.13   228.7  662.33   236.2  662.36   238.7  662.37   268.5  663.73
   308.3  665.26   318.3  666.02   328.2  667.77   338.2  670.72   348.1  674.24
     358  677.33     368  678.99   377.9  682.12   387.9  686.77   407.8  697.55
#Mann= 3 , 0 , 0
       0     .08       0   221.2    .045       0   236.2     .08       0
Bank Sta=221.2,236.2
XS Rating Curve= 0 ,0
Exp/Cntr=0.3,0.1

Type RM Length L Ch R = 1 ,4889.6  ,283.9,286.9,289.9
XS GIS Cut Line= 2
     1550526.586      402622.999     1550691.138      402855.904
#Sta/Elev= 23
     9.8  708.01    49.2  687.35    68.8  676.83    78.7   671.7    88.5  667.33
    98.3  665.25   108.2  664.32     118  663.59   127.8  662.75   147.5  660.87
   149.8  660.78   157.3  660.49   164.8  660.61   167.2  660.66     177   661.4
   186.8  662.49   196.7  664.48   206.5  667.11   216.3  669.97     236  675.06
   245.8  679.16   255.7  684.21   285.2  700.25
#Mann= 3 , 0 , 0
       0     .08       0   149.8    .045       0   164.8     .08       0
Bank Sta=149.8,164.8
XS Rating Curve= 0 ,0
Exp/Cntr=0.3,0.1

Type RM Length L Ch R = 1 ,4602.8  ,542,538.5,534.9
XS GIS Cut Line= 2
     1550283.556      402701.478     1550410.134      402964.761
#Sta/Elev= 26
    10.1  695.55    30.2  686.36    40.3  681.81    50.4  677.38    60.4  673.21
    70.5  669.28    80.6  665.82    90.7  663.31   100.7  661.93   120.9  660.18
     141  658.32   151.1  657.72   153.7  657.71   161.2  657.68   168.7  658.13
   171.2  658.28   181.3  659.47   201.5  662.43   211.5  664.21   221.6  666.44
   231.7   668.8   241.8  670.14   251.8  673.26   261.9  678.35   282.1  689.35
   292.1  694.94
#Mann= 3 , 0 , 0
       0      .1       0   153.7    .045       0   168.7     .08       0
Bank Sta=153.7,168.7
XS Rating Curve= 0 ,0
Exp/Cntr=0.3,0.1

Type RM Length L Ch R = 1 ,4064.3  ,256.2,281.9,307.5
XS GIS Cut Line= 2
     1549810.153      402944.508     1550053.183      403281.207
#Sta/Elev= 30
    10.1  712.34    30.4  705.27    40.5  702.08    50.6  699.13    70.9  693.59
    91.2  687.72   121.5   679.7   131.7  675.75   151.9  666.89   172.2     656
   182.3  653.24   184.9  653.22   192.4  653.18   199.9  654.38   202.6   654.8
   222.8  659.41   232.9   660.9   243.1  661.96   253.2  662.58   263.3  662.95
   303.8  662.85     314  662.63   324.1  663.58   334.2  665.75   344.4  668.27
   354.5  670.15   364.6   672.3   374.7  675.24   384.9  677.88   415.2  684.74
#Mann= 3 , 0 , 0
       0     .08       0   184.9    .045       0   199.9     .08       0
Bank Sta=184.9,199.9
XS Rating Curve= 0 ,0
Exp/Cntr=0.3,0.1

Type RM Length L Ch R = 1 ,3782.4  ,310.3,297.8,285.3
XS GIS Cut Line= 4
      1549756.99      402891.346     1549743.874      403022.732
     1549659.976      403173.437     1549629.734      403356.166
#Sta/Elev= 30
    10.2  728.62    30.5  717.37    71.1  694.29    91.4  683.11   101.6  677.74
   111.7   672.7   121.9  668.07     132  663.99   142.2  660.51   152.3  659.04
   162.5  658.28   243.6  652.81   256.4  652.16   263.9   652.1   271.4  653.95
   274.1  654.61   284.2  660.84   294.4  668.61   304.5  674.27   314.3   676.9
     324  679.22   333.8  682.73   343.5  687.87   353.3  694.03     363  699.69
   372.8  704.66   421.5  728.49     441  737.67   470.2  750.07   489.7  758.93
#Mann= 3 , 0 , 0
       0     .06       0   256.4    .045       0   271.4     .06       0
Bank Sta=256.4,271.4
XS Rating Curve= 0 ,0
Exp/Cntr=0.3,0.1

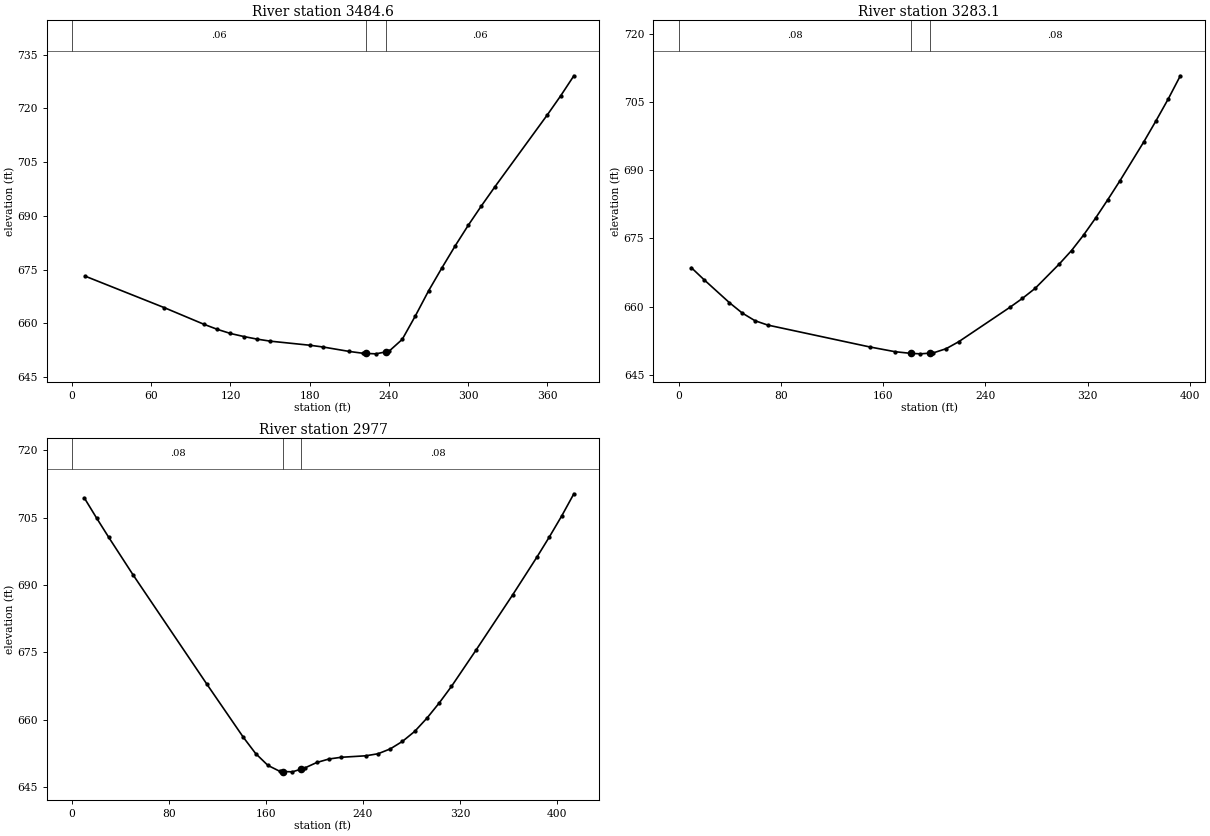
Type RM Length L Ch R = 1 ,3484.6  ,201.1,201.5,203.5
XS GIS Cut Line= 2
     1549394.976       402817.93     1549412.697      403197.665
#Sta/Elev= 27
      10  673.18      70  664.38     100  659.74     110  658.35     120  657.19
   130.1  656.34   140.1  655.62   150.1  655.05   180.1  653.91   190.1  653.42
   210.1  652.17   220.1  651.68   222.6  651.63   230.1  651.51   237.6  652.05
   240.1  652.24   250.1  655.55   260.1  662.14   270.1  669.13   280.1  675.47
   290.1  681.59   300.1  687.39   310.1  692.83   320.1  698.04   360.1  718.26
   370.1  723.52   380.1  729.12
#Mann= 3 , 0 , 0
       0     .06       0   222.6    .045       0   237.6     .06       0
Bank Sta=222.6,237.6
XS Rating Curve= 0 ,0
Exp/Cntr=0.3,0.1

Type RM Length L Ch R = 1 ,3283.1  ,324.6,306.1,286
XS GIS Cut Line= 3
     1549220.298       402866.03     1549205.108      403144.502
     1549275.992      403233.107
#Sta/Elev= 27
      10   668.6    19.9  665.97    39.8  660.91    49.8  658.64    59.8  656.95
    69.7     656   149.4   651.2   169.3  650.15   181.7  649.78   189.2  649.68
   196.7  649.84   199.2  649.89   209.2   650.8   219.1  652.34     259  659.87
   268.9  661.85   278.9  664.06   297.8  669.42   307.3  672.35   316.7  675.74
   326.2  679.51   335.6  683.49   345.1  687.64     364  696.29   373.4  700.85
   382.9  705.61   392.4  710.72
#Mann= 3 , 0 , 0
       0     .08       0   181.7    .045       0   196.7     .08       0
Bank Sta=181.7,196.7
XS Rating Curve= 0 ,0
Exp/Cntr=0.3,0.1

Type RM Length L Ch R = 1 ,2977    ,2951.1,2977,3000.5
XS GIS Cut Line= 2
     1548850.689      403025.519     1549157.008      403303.991
#Sta/Elev= 30
    10.1  709.38    20.2  704.92    30.3  700.59    50.5  692.19   111.1  667.99
   141.4  656.09   151.5   652.5   161.6  649.87   171.6  648.53   174.2  648.51
   181.7  648.44   189.2  649.06   191.8  649.28   201.9  650.52     212   651.3
   222.1  651.68   242.3  652.01   252.4  652.46   262.5  653.54   272.6  655.22
   282.7  657.44   292.8  660.39   302.9  663.76     313  667.44   333.2  675.49
   363.5  687.81   383.7  696.29   393.8  700.71   403.9  705.33     414   710.3
#Mann= 3 , 0 , 0
       0     .08       0   174.2    .045       0   189.2     .08       0
Bank Sta=174.2,189.2
XS Rating Curve= 0 ,0
Exp/Cntr=0.3,0.1

Chan Stop Cuts=-1
Use User Specified Reach Order=0